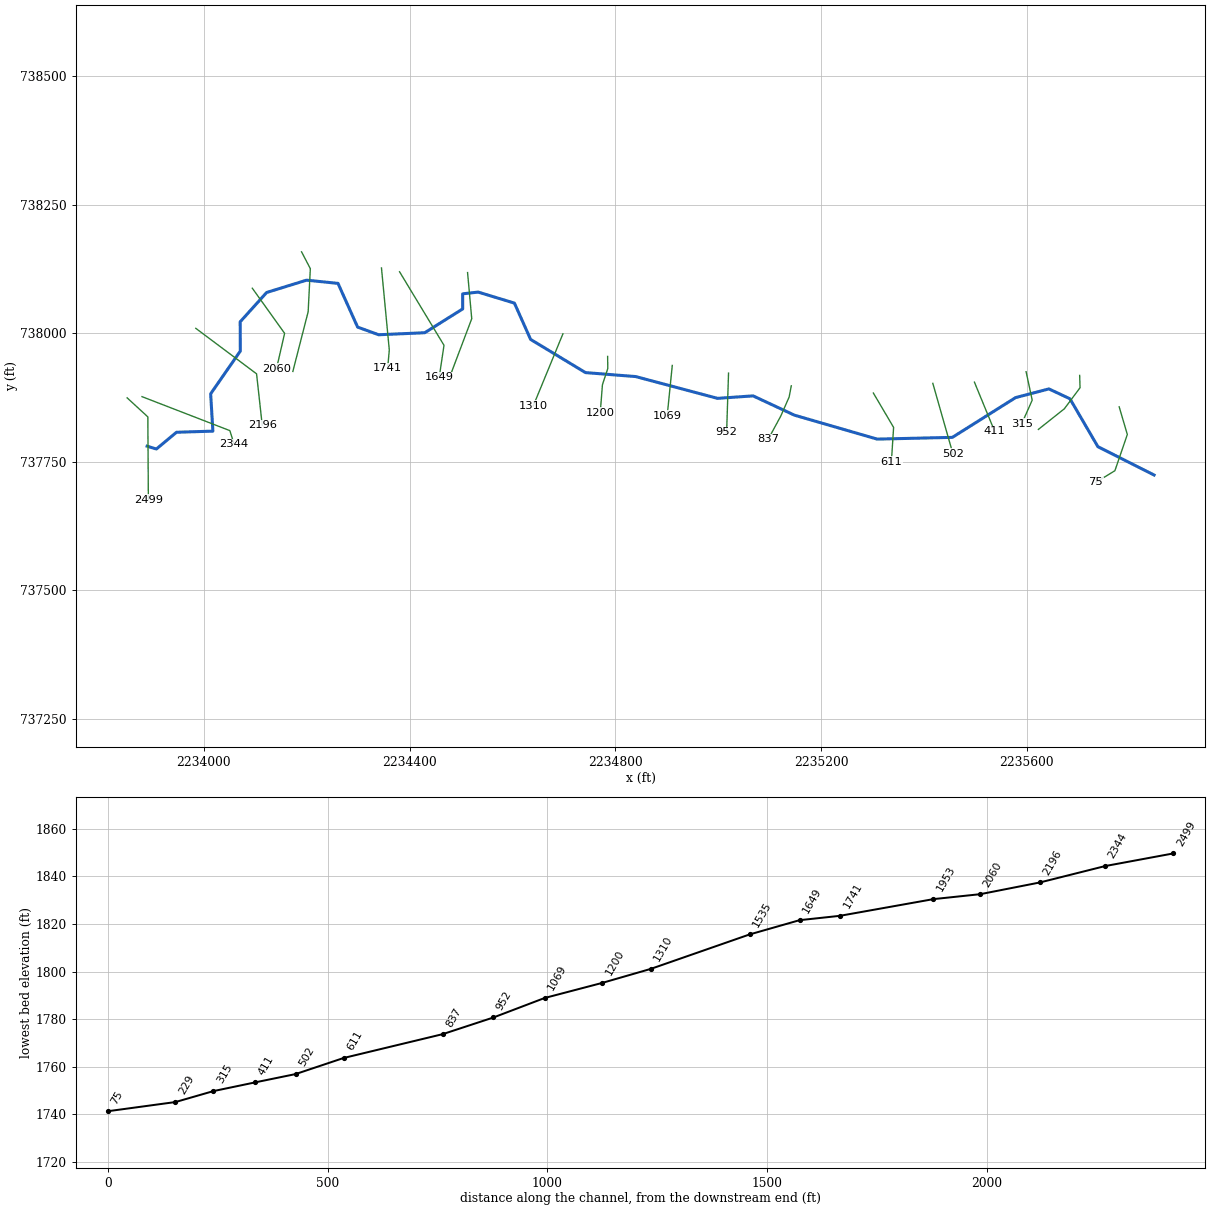
--- SWAMPRN2.prj (project) ---

Proj Title=SWAMPRN2
Current Plan=p01
Default Exp/Contr=0,0
English Units
Geom File=g01
Flow File=f01
Plan File=p01
BEGIN DESCRIPTION:
---------- MODELED AS PART OF WVEMD CTP PROGRAM, 2023----------
Stream Name: Swamp Run (II)
Flood Zone:  AFH
Upshur County, WV
HEC-RAS Version: RAS 6.3
Vertical Datum: NAVD88
Projection: NAD 1983 StatePlane West Virginia S FIPS 4702 (US Feet)
Terrain: 1-meter LIDAR (FEMA Region III 3DEP collected 2016-2018)
Land Use: 2019 NLCD
Hydrologic Method:
WV 2010 Regional Regression Equations
Additional Model Notes:
None
END DESCRIPTION:
DSS Export Rating Curves= 0
DSS Export Rating Curve Sorted= 0
DSS Export Volume Flow Curves= 0
DXF OffsetX= 0
DXF OffsetY= 0
DXF ScaleX= 0
DXF ScaleY= 0

--- SWAMPRN2.p01 (plan) ---

Plan Title=Floodplain
Program Version=4.00
Geom File=g01
Flow File=f01
K Sum by GR=0
Std Step Tol=0.01
Critical Tol=0.01
Num of Std Step Trials=20
Max Error Tol=0.3
Flow Tol Ratio=0.001
Split Flow NTrial=30
Split Flow Tol=0.02
Split Flow Ratio=0.02
Log Output Level=0
Friction Slope Method=1
Unsteady Friction Slope Method=2
Unsteady Bridges Friction Slope Method=1
Global Log Level=0
CheckData=False
Run HTab=0
Run UNet=0
Run PostProcess=0
UNET Theta=0
UNET Theta Warmup=0
UNET ZTol=0
UNET ZSATol=0
UNET MxIter=0
UNET MaxInSteps=0
UNET DtIC=0
UNET DtMin=0
UNET MaxCRTS=0
UNET WFStab=0
UNET SFStab=0
UNET WFX=0
UNET SFX=0
UNET DSS MLevel=0
UNET DZMax Abort=0
UNET Convert EG Bridges=0
UNET Use Existing IB Tables=0
UNET Froude Limit=0
UNET Froude Power=0
Write IC File=0
Echo Input=False
Echo Output=False
Write Detailed=0

--- SWAMPRN2.f01 (steady flow) ---

Flow Title=Flows
Program Version=6.31
Number of Profiles= 1
Profile Names=01pct
River Rch & RM=SWAMPRN2,Main            ,2499
     345
Boundary for River Rch & Prof#=SWAMPRN2,Main            , 1
Up Type= 0
Dn Type= 3
Dn Slope=0.02511
DSS Import GetInterval= 0
DSS Import GetPeak= 0
DSS Import FillOption= 0

--- SWAMPRN2.g01 (geometry) ---

Geom Title=Geometry
Program Version=6.31

River Reach=SWAMPRN2        ,Main
Reach XY= 30
2233889.70688096737780.456019554     2233907.695      737775.001
     2233946.785      737807.567     2234017.496      737809.742
     2234013.175      737882.341     2234070.866      737965.472
     2234070.551      738022.247      2234122.06      738079.336
     2234199.611      738103.231     2234260.735      738097.021
     2234298.881      738012.002     2234339.831      737997.122
       2234429.4      738001.042     2234503.088      738047.286
     2234503.088      738076.675     2234533.249      738080.052
     2234603.731      738058.618     2234635.209      737988.022
     2234741.863      737923.549      2234839.33      737915.851
 2234998.6454702737873.457820422      2235067.66      737878.306
2235147.97705166737840.826104472     2235309.011      737794.231
     2235455.126      737797.637     2235577.976      737874.901
     2235642.821      737891.842     2235683.714       737872.64
     2235737.999       737779.58     2235847.257      737724.436

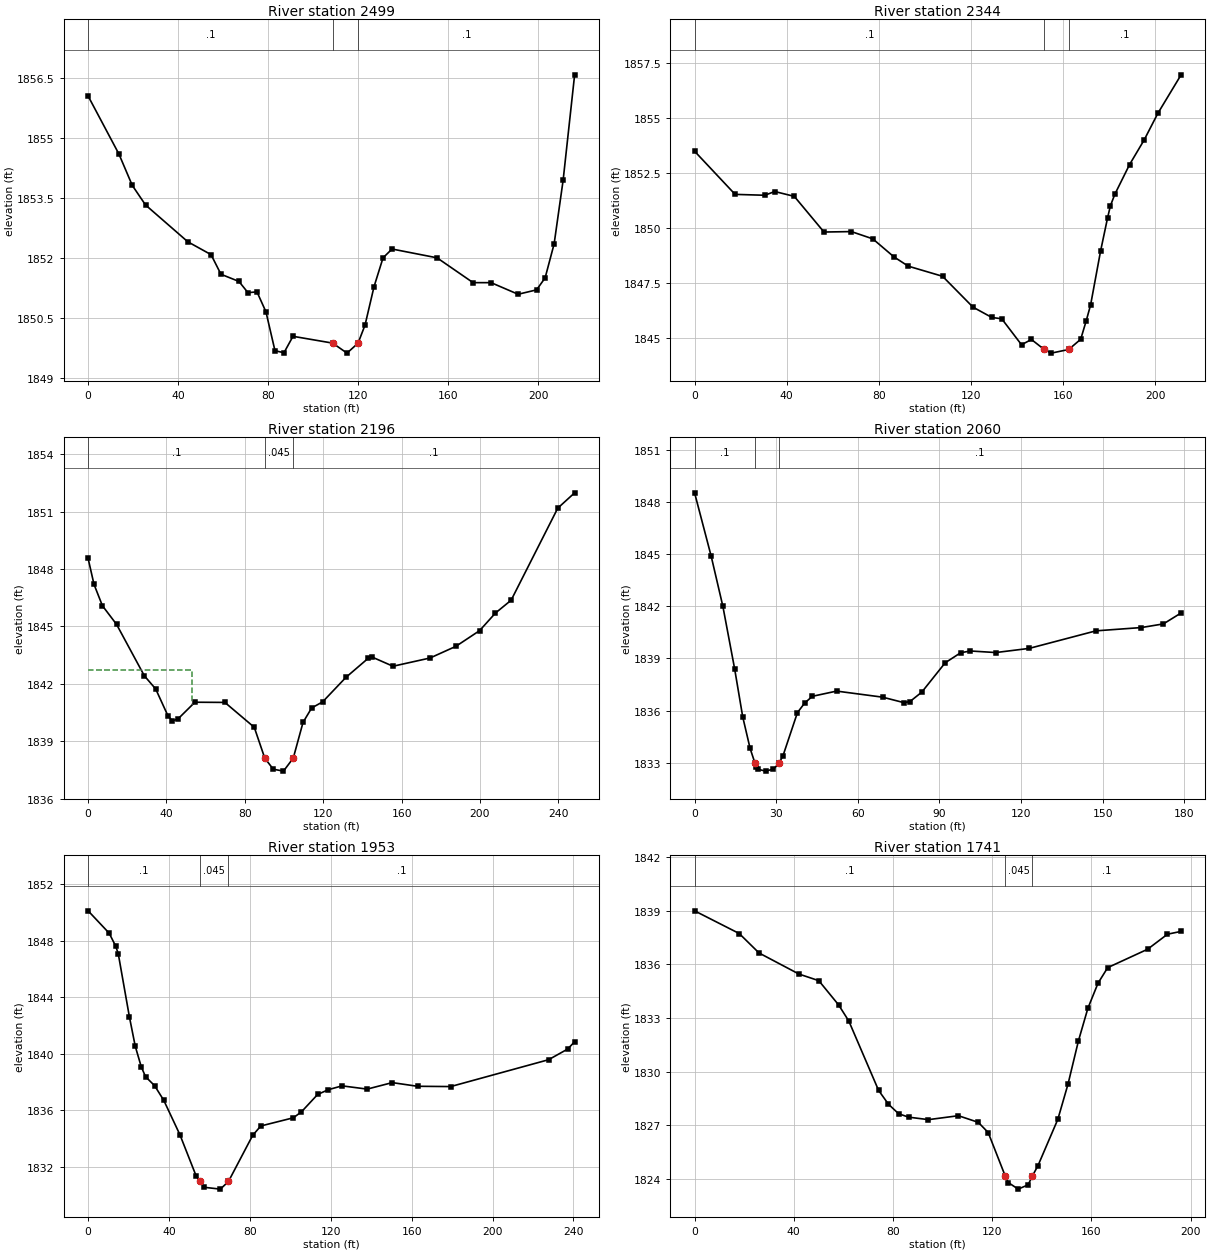
Type RM Length L Ch R = 1 ,2499    ,155.2,155.2,155.2
XS GIS Cut Line= 3
2233850.81089577737874.4625344922233891.04173988737837.493195266
 2233892.0718075737676.069288135
#Sta/Elev= 30
       0 1856.05    13.7  1854.6    19.6 1853.82    25.5 1853.33    44.3 1852.41
    54.6 1852.09      59  1851.6      67 1851.42      71 1851.14      75 1851.16
      79 1850.66      83 1849.69      87 1849.64      91 1850.05  108.63 1849.88
     115 1849.63  119.91 1849.88     123 1850.33     127 1851.29     131 1852.01
     135 1852.23     155 1852.01     171 1851.39     179 1851.39     191  1851.1
   199.2 1851.21     203 1851.51     207 1852.36     211 1853.95   216.1 1856.58
#Mann= 3 ,-1,0
       0      .1       0  108.63    .045       0  119.91      .1       0
Bank Sta=108.63,119.91
XS Rating Curve= 0 ,0
Exp/Cntr(USF)=0,0
Exp/Cntr=0.3,0.1

Type RM Length L Ch R = 1 ,2344    ,151.2,148.4,143.9
XS GIS Cut Line= 3
2233879.72609225737876.7805972772234050.52077857737810.724879399
2234058.91154795737783.874417357
#Sta/Elev= 30
       0 1853.49    17.6 1851.53    30.5 1851.49    34.8 1851.66    43.3 1851.44
    56.2 1849.82    68.1 1849.84    77.4 1849.51    86.6 1848.69    92.8 1848.27
   107.7 1847.81   120.9 1846.41   129.1 1845.94   133.4 1845.88     142  1844.7
   146.3 1844.94  151.831844.487   154.9 1844.32  162.481844.485   167.7 1844.95
   170.1 1845.79     172 1846.51   176.3 1848.94   179.4 1850.48   180.6 1851.01
   182.5 1851.53   188.9 1852.88   195.3 1854.01   201.2 1855.21   211.3 1856.96
#Mann= 3 ,-1,0
       0      .1       0  151.83    .045       0  162.48      .1       0
Bank Sta=151.83,162.48
XS Rating Curve= 0 ,0
Exp/Cntr(USF)=0,0
Exp/Cntr=0.3,0.1

Type RM Length L Ch R = 1 ,2196    ,137,135.9,132.8
XS GIS Cut Line= 3
2233984.32693117738009.5688489362234102.41924108737921.172266084
2234113.46881393737821.035512071
#Sta/Elev= 30
       0 1848.55       3  1847.2     7.3 1846.08    14.5 1845.11    28.7 1842.42
    34.5 1841.73    40.7 1840.34      43 1840.06    45.9 1840.17    54.5 1841.04
    69.8 1841.03    84.8 1839.73   90.161838.118    94.5 1837.54    99.7 1837.44
   104.7 1838.12   109.7 1839.99   114.1 1840.74   119.7 1841.06   131.6 1842.34
     143 1843.34   144.7 1843.41   155.6 1842.92   174.5 1843.35   187.7 1843.96
   199.8 1844.78   207.9  1845.7   215.9 1846.37   239.7 1851.18   248.3 1851.98
#Mann= 3 ,-1,0
       0      .1       0   90.16    .045       0   104.7      .1       0
#XS Ineff= 2 , 0
           52.81 1842.72
Permanent Ineff=
       F       F
Bank Sta=90.16,104.7
XS Rating Curve= 0 ,0
Exp/Cntr(USF)=0,0
Exp/Cntr=0.3,0.1

Type RM Length L Ch R = 1 ,2060    ,112.5,106.6,97.7
XS GIS Cut Line= 3
2234094.13206143738087.6064572362234156.97650706737999.900472687
2234141.09274608737930.840642333
#Sta/Elev= 30
       0 1848.54     6.1 1844.89    10.4    1842    14.7 1838.42    17.7 1835.63
    20.4 1833.82   22.211832.962    22.7 1832.73    23.3 1832.62    26.1 1832.51
      29 1832.63      31 1832.96    32.5  1833.4    37.8 1835.88    40.5 1836.44
    43.3 1836.82    52.2 1837.12    69.1 1836.77    76.8 1836.46    79.1 1836.51
    83.5 1837.06    92.1 1838.75    97.8 1839.33   101.4 1839.43   110.7 1839.34
     123 1839.58   147.5 1840.59   164.2 1840.78   172.3 1840.99   178.8 1841.62
#Mann= 3 ,-1,0
       0      .1       0   22.21    .045       0      31      .1       0
Bank Sta=22.21,31
XS Rating Curve= 0 ,0
Exp/Cntr(USF)=0,0
Exp/Cntr=0.3,0.1

Type RM Length L Ch R = 1 ,1953    ,211.1,212.7,210.9
XS GIS Cut Line= 4
2234189.86494499738158.3590432672234206.95989968738125.657741998
2234202.72595519738041.8777716162234172.97502076737925.789762283
#Sta/Elev= 30
       0 1850.13    10.4 1848.55    13.6 1847.64    14.9  1847.1    20.4 1842.64
    23.3 1840.55    26.3 1839.08    28.4 1838.39    32.9 1837.75    37.4 1836.72
    45.4 1834.28    53.4 1831.37    55.4 1830.97    57.4 1830.56    65.4 1830.43
    69.4 1830.97    81.4 1834.24    85.4  1834.9   101.5 1835.48   105.5  1835.9
   113.5 1837.13   118.8 1837.47   125.6 1837.74     138 1837.51   150.4 1837.97
   162.9 1837.71   179.3 1837.69   227.7 1839.59   237.1 1840.34   240.6 1840.86
#Mann= 3 ,-1,0
       0      .1       0    55.4    .045       0    69.4      .1       0
Bank Sta=55.4,69.4
XS Rating Curve= 0 ,0
Exp/Cntr(USF)=0,0
Exp/Cntr=0.3,0.1

Type RM Length L Ch R = 1 ,1741    ,87,91.8,96.4
XS GIS Cut Line= 3
 2234345.2596914738127.0601702242234360.46572605737967.468687022
 2234357.2424023 737931.68035114
#Sta/Elev= 30
       0    1839      18 1837.73      26 1836.64    42.1 1835.46    50.1 1835.09
    58.1 1833.73    62.2 1832.83    74.2 1828.95    78.2 1828.17    82.3 1827.64
    86.3 1827.45    94.3 1827.31   106.4 1827.53   114.4 1827.16   118.4 1826.59
  125.32 1824.14   126.5 1823.79   130.5 1823.42   134.5 1823.66  136.17 1824.14
   138.5 1824.74   146.5 1827.33   150.6  1829.3   154.8 1831.72   158.6 1833.54
   162.7 1834.95   166.6 1835.82   182.7 1836.85   190.7 1837.69   196.2 1837.85
#Mann= 3 ,-1,0
       0      .1       0  125.32    .045       0  136.17      .1       0
Bank Sta=125.32,136.17
XS Rating Curve= 0 ,0
Exp/Cntr(USF)=0,0
Exp/Cntr=0.3,0.1

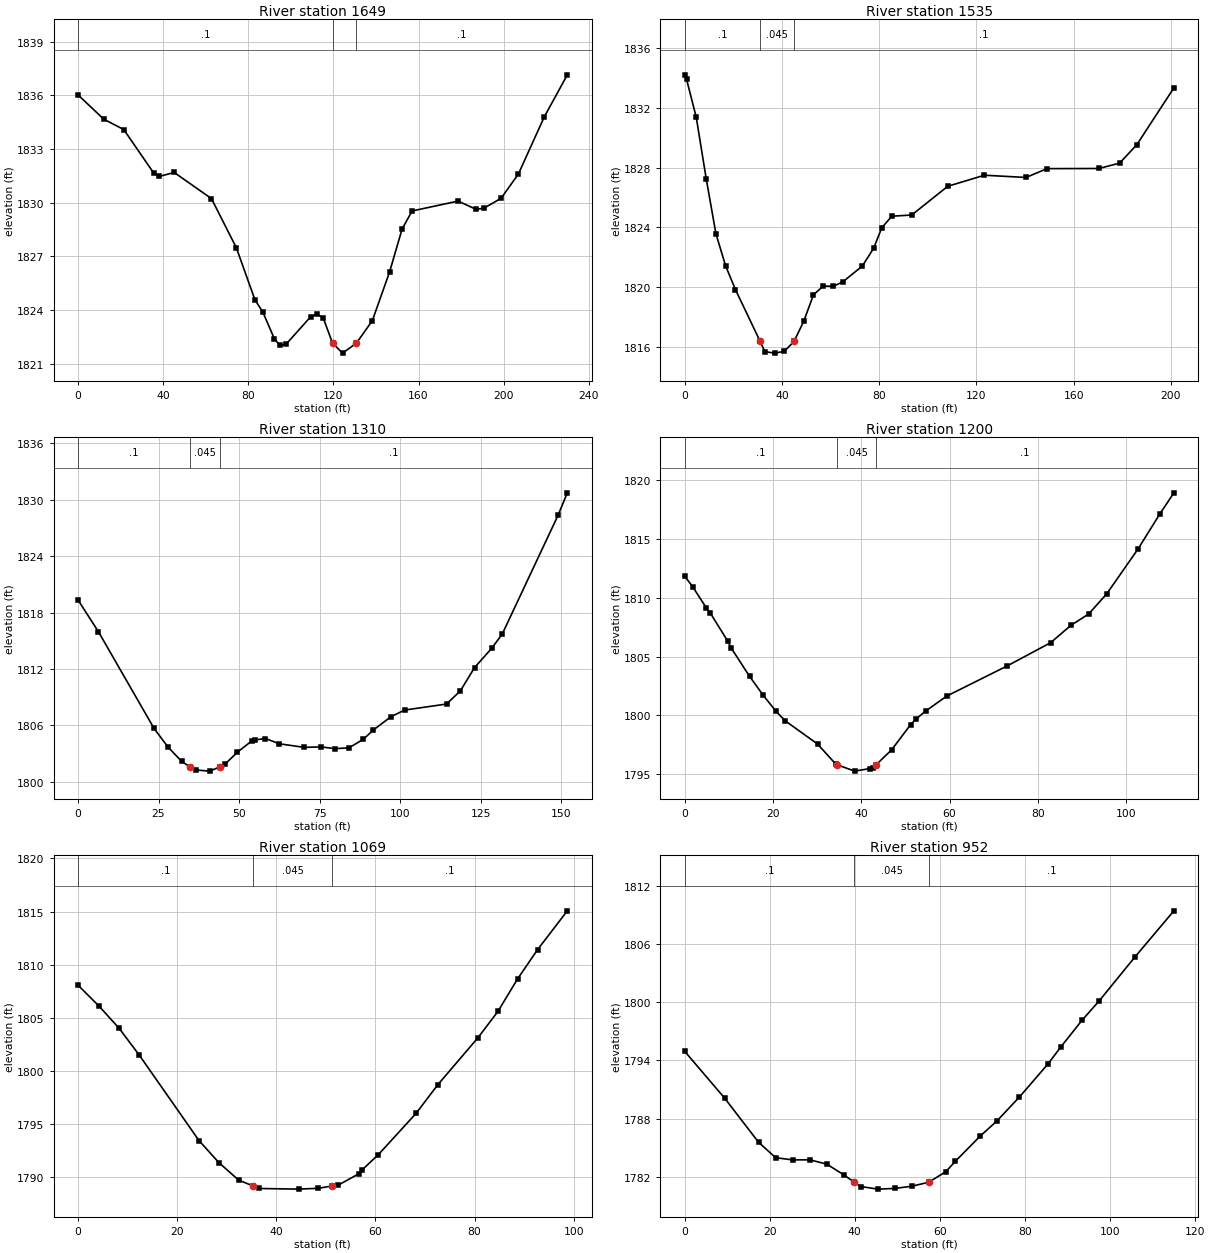
Type RM Length L Ch R = 1 ,1649    ,117.4,113.6,105
XS GIS Cut Line= 3
2234380.42718475738119.5583689462234466.82103252737976.604520114
2234457.49795542737914.450672795
#Sta/Elev= 30
       0 1836.03    12.1 1834.67    21.5 1834.09    35.5 1831.67    38.2 1831.47
    45.2 1831.69    62.7 1830.23    74.4 1827.48    83.1 1824.58    86.9 1823.87
    92.3 1822.38    94.8 1822.03    97.7 1822.08   109.3 1823.62   112.2 1823.77
   115.2 1823.56   119.6 1822.15   124.3 1821.59  130.821822.148   138.3 1823.41
   146.4 1826.13   152.3 1828.54     157 1829.54   178.6 1830.09     187 1829.63
   190.7 1829.69   198.8 1830.25   206.9  1831.6     219 1834.78   229.9 1837.15
#Mann= 3 ,-1,0
       0      .1       0   119.6    .045       0  130.82      .1       0
Bank Sta=119.6,130.82
XS Rating Curve= 0 ,0
Exp/Cntr(USF)=0,0
Exp/Cntr=0.3,0.1

Type RM Length L Ch R = 1 ,1535    ,230.1,224.9,216.6
XS GIS Cut Line= 3
2234512.62685858738117.9972927462234520.73621596738028.350658838
2234481.46325571737924.323028696
#Sta/Elev= 30
       0  1834.2      .8 1833.91     4.8 1831.36     8.9 1827.25    12.9 1823.57
    16.9 1821.42    20.9 1819.85   31.09 1816.38      33  1815.7      37  1815.6
      41 1815.72      45 1816.38      49 1817.73      53  1819.5    57.1 1820.09
    61.1 1820.06    65.1 1820.37    73.1 1821.42    77.7  1822.6    81.1 1823.98
    85.2 1824.75    93.4 1824.83   108.2 1826.75   123.3 1827.49   140.4 1827.34
     149 1827.93   170.4 1827.94   178.9  1828.3     186 1829.54   201.2 1833.33
#Mann= 3 ,-1,0
       0      .1       0   31.09    .045       0      45      .1       0
Bank Sta=31.09,45
XS Rating Curve= 0 ,0
Exp/Cntr(USF)=0,0
Exp/Cntr=0.3,0.1

Type RM Length L Ch R = 1 ,1310    ,109.4,110.4,110.5
XS GIS Cut Line= 2
2234698.03334455737998.9799051482234640.23026654737858.512210209
#Sta/Elev= 30
       0 1819.35     6.3 1815.99    23.6 1805.68    27.9 1803.71    32.2 1802.16
    34.81801.569    36.6 1801.25    40.9 1801.13      44 1801.58    45.7 1801.89
    49.5 1803.15    53.9 1804.33    54.9 1804.45    58.2  1804.6    62.5 1804.04
    70.2 1803.66    75.5 1803.71    79.8 1803.52    84.1 1803.61    88.5  1804.5
    91.7 1805.51    97.1 1806.91   101.4 1807.63   114.4 1808.27   118.7 1809.67
   123.1 1812.15   128.4 1814.19   131.7 1815.72     149 1828.34   151.9 1830.75
#Mann= 3 ,-1,0
       0      .1       0    34.8    .045       0      44      .1       0
Bank Sta=34.8,44
XS Rating Curve= 0 ,0
Exp/Cntr(USF)=0,0
Exp/Cntr=0.3,0.1

Type RM Length L Ch R = 1 ,1200    ,127.7,131.2,133
XS GIS Cut Line= 4
2234784.91296252737954.9359858032234785.24786272737931.507945078
2234774.82622988737899.988860376 2234770.6210788737845.938670132
#Sta/Elev= 30
       0 1811.86     1.8 1810.97     4.9 1809.17     5.8 1808.73     9.8  1806.3
    10.6 1805.71    14.7 1803.33    17.8 1801.71    20.7 1800.35    22.8 1799.53
    30.1 1797.56    34.3 1795.82   34.56 1795.79    38.5 1795.25      42 1795.47
    42.7 1795.55   43.37 1795.79    46.9 1797.07    51.2 1799.22    52.3 1799.65
    54.6 1800.37    59.4 1801.65    72.9 1804.18    82.9 1806.19    87.5 1807.67
    91.5 1808.63    95.6 1810.35   102.7 1814.18   107.6 1817.14   110.8 1818.95
#Mann= 3 ,-1,0
       0      .1       0   34.56    .045       0   43.37      .1       0
Bank Sta=34.56,43.37
XS Rating Curve= 0 ,0
Exp/Cntr(USF)=0,0
Exp/Cntr=0.3,0.1

Type RM Length L Ch R = 1 ,1069    ,114.8,116.3,117.3
XS GIS Cut Line= 2
2234910.59950237737937.447596303 2234900.6548868 737839.24451754
#Sta/Elev= 23
       0 1808.08     4.3 1806.08     8.3 1804.02    12.3 1801.54    24.4 1793.47
    28.4  1791.4    32.4 1789.75    35.3  1789.2    36.5 1788.96    44.5  1788.9
    48.5 1788.98    51.3  1789.2    52.5 1789.28    56.6 1790.33    57.2 1790.66
    60.6 1792.15    68.2 1796.03    72.6 1798.73    80.7 1803.15    84.7 1805.61
    88.7 1808.69    92.7 1811.42    98.7 1815.07
#Mann= 3 ,-1,0
       0      .1       0    35.3    .045       0    51.3      .1       0
Bank Sta=35.3,51.3
XS Rating Curve= 0 ,0
Exp/Cntr(USF)=0,0
Exp/Cntr=0.3,0.1

Type RM Length L Ch R = 1 ,952     ,119.7,115.4,110.7
XS GIS Cut Line= 2
2235019.99027365737922.5306729472235016.26104282737807.546055408
#Sta/Elev= 25
       0 1794.94     9.4 1790.11    17.4 1785.55    21.4 1783.97    25.4 1783.74
    29.4 1783.75    33.4 1783.31    37.4 1782.21    39.9 1781.43    41.4    1781
    45.4 1780.73    49.4  1780.8    53.4 1781.03    57.4 1781.44    61.4 1782.53
    63.6 1783.58    69.4 1786.16    73.4 1787.75    78.7 1790.22    85.4 1793.62
    88.4 1795.36    93.4 1798.12    97.4  1800.1   105.8 1804.62     115  1809.4
#Mann= 3 ,-1,0
       0      .1       0    39.9    .045       0    57.4      .1       0
Bank Sta=39.9,57.4
XS Rating Curve= 0 ,0
Exp/Cntr(USF)=0,0
Exp/Cntr=0.3,0.1

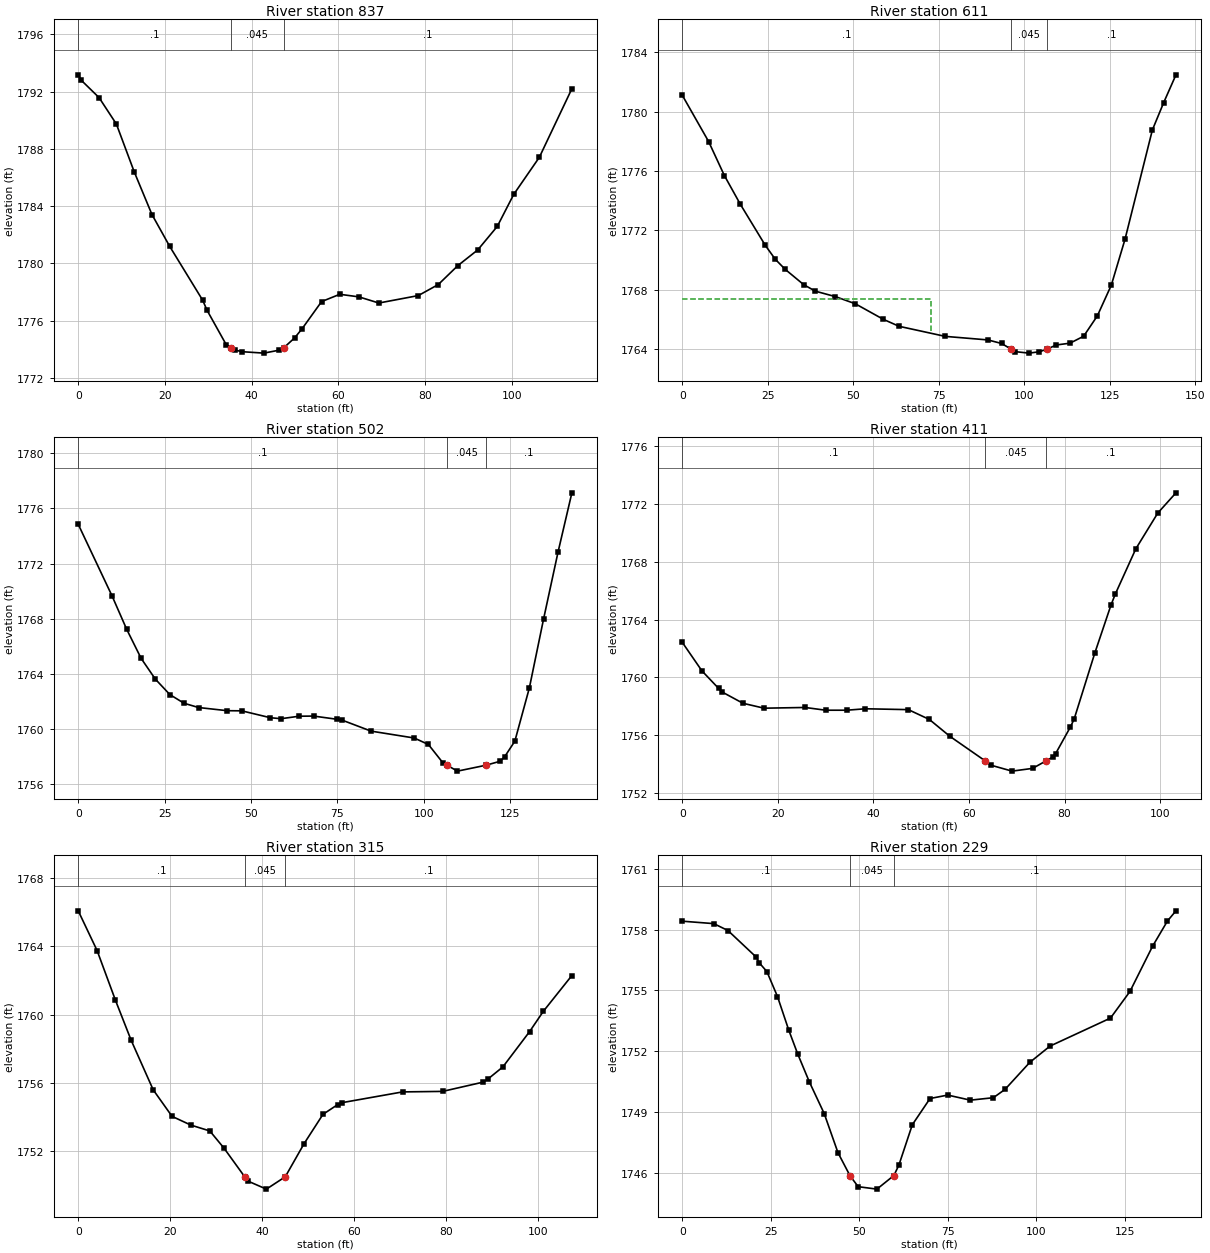
Type RM Length L Ch R = 1 ,837     ,220,225.5,228.1
XS GIS Cut Line= 4
2235141.98594008737897.8658618232235137.80407629737876.095360682
2235121.53616161737838.9841803062235097.14810717737794.093289519
#Sta/Elev= 30
       0 1793.17      .7 1792.79     4.8 1791.58     8.8 1789.73    12.9  1786.4
      17 1783.41    21.1 1781.18    28.7 1777.42    29.7 1776.72    34.1 1774.33
    35.2 1774.11    36.2 1773.94    37.8 1773.83    42.8 1773.73    46.2 1773.93
   47.41 1774.11    49.9  1774.8    51.6 1775.43    56.1 1777.33    60.3 1777.84
    64.7 1777.66    69.3 1777.23    78.4 1777.75      83 1778.52    87.5 1779.84
    92.1 1780.94    96.6 1782.58   100.4 1784.82   106.3 1787.41   113.8  1792.2
#Mann= 3 ,-1,0
       0      .1       0    35.2    .045       0   47.41      .1       0
Bank Sta=35.2,47.41
XS Rating Curve= 0 ,0
Exp/Cntr(USF)=0,0
Exp/Cntr=0.3,0.1

Type RM Length L Ch R = 1 ,611     ,105.9,109.2,113.1
XS GIS Cut Line= 3
2235301.54370084 737883.80031039 2235340.8921007737817.018905462
2235336.59003682737750.253100321
#Sta/Elev= 30
       0  1781.1     7.7 1777.98    12.3 1775.69      17 1773.74    24.3 1770.97
    27.2 1770.04    30.1 1769.36    35.5 1768.33    38.9 1767.89    44.8 1767.52
    50.6 1767.04    58.8 1765.99    63.4 1765.52    76.9 1764.84    89.4  1764.6
    93.4 1764.36   96.25 1763.97    97.4 1763.81   101.4 1763.71   104.4  1763.8
   106.6 1763.97   109.4 1764.26   113.4 1764.38   117.4 1764.85   121.4 1766.22
   125.5  1768.3   129.5 1771.39   137.5 1778.76   140.8  1780.6   144.4 1782.48
#Mann= 3 ,-1,0
       0      .1       0   96.25    .045       0   106.6      .1       0
#XS Ineff= 2 , 0
           72.78 1767.35
Permanent Ineff=
       F       F
Bank Sta=96.25,106.6
XS Rating Curve= 0 ,0
Exp/Cntr(USF)=0,0
Exp/Cntr=0.3,0.1

Type RM Length L Ch R = 1 ,502     ,90.3,91.3,92.3
XS GIS Cut Line= 2
2235417.15335802737902.6414418052235456.31028183737765.281439231
#Sta/Elev= 30
       0 1774.85     9.8 1769.65      14 1767.25    18.2 1765.13    22.3 1763.63
    26.5 1762.51    30.6 1761.88    34.8 1761.57    43.1 1761.34    47.3 1761.33
    55.6 1760.83    58.7 1760.76    63.9 1760.94    68.1 1760.95    74.8 1760.72
    76.4 1760.65    84.7 1759.86    97.2 1759.36   101.3 1758.89   105.5 1757.56
  106.721757.381   109.7 1756.96     118 1757.39   122.1 1757.68   123.4 1758.02
   126.3 1759.13   130.5 1762.99   134.6 1767.97   138.8 1772.84   142.8 1777.13
#Mann= 3 ,-1,0
       0      .1       0  106.72    .045       0     118      .1       0
Bank Sta=106.72,118
XS Rating Curve= 0 ,0
Exp/Cntr(USF)=0,0
Exp/Cntr=0.3,0.1

Type RM Length L Ch R = 1 ,411     ,96.9,95.9,94.1
XS GIS Cut Line= 2
2235498.02132141737904.9622229532235537.31926525737809.475131532
#Sta/Elev= 28
       0 1762.42     4.1 1760.45     7.6 1759.23     8.4 1758.97    12.7  1758.2
    17.1 1757.86    25.7 1757.91      30 1757.72    34.4 1757.72    38.3 1757.82
    47.3 1757.76    51.7 1757.08      56 1755.91   63.34 1754.22    64.6 1753.91
      69  1753.5    73.3 1753.69   76.17 1754.22    77.6 1754.49    78.1  1754.7
    81.2 1756.55      82 1757.11    86.3 1761.66    89.7    1765    90.6 1765.76
    94.9  1768.9    99.5 1771.38   103.3 1772.78
#Mann= 3 ,-1,0
       0      .1       0   63.34    .045       0   76.17      .1       0
Bank Sta=63.34,76.17
XS Rating Curve= 0 ,0
Exp/Cntr(USF)=0,0
Exp/Cntr=0.3,0.1

Type RM Length L Ch R = 1 ,315     ,93.7,86,76.3
XS GIS Cut Line= 3
2235598.51224365737925.1647049312235610.33616066737869.994892675
2235589.66436131737823.538333058
#Sta/Elev= 25
       0 1766.06     4.1 1763.74     8.1 1760.83    11.5  1758.5    16.3  1755.6
    20.4 1754.05    24.5 1753.54    28.6  1753.2    31.7 1752.19   36.16 1750.53
    36.8 1750.28    40.9  1749.8      45 1750.52    49.1 1752.46    53.2 1754.17
56.422631754.743    57.3 1754.85    70.5 1755.48    79.2 1755.51      88 1756.05
      89 1756.22    92.3 1756.94    98.1    1759   101.1 1760.19   107.3 1762.28
#Mann= 3 ,-1,0
       0      .1       0   36.16    .045       0      45      .1       0
Bank Sta=36.16,45
XS Rating Curve= 0 ,0
Exp/Cntr(USF)=0,0
Exp/Cntr=0.3,0.1

Type RM Length L Ch R = 1 ,229     ,77.7,154,72.4
XS GIS Cut Line= 4
2235702.60573927 737918.036078232235703.36829777737894.142578536
2235672.86595774737853.2186056562235622.28291051737813.057191277
#Sta/Elev= 30
       0 1758.41     8.9 1758.29    12.9 1757.95    20.9 1756.64    21.7 1756.37
    23.9 1755.93    26.9  1754.7    30.1 1753.04    32.6 1751.88    35.9  1750.5
    40.1 1748.94      44 1747.01    47.41745.877    49.7 1745.34      55 1745.22
   59.79 1745.89    61.2  1746.4      65 1748.39      70 1749.68      75 1749.85
    81.4  1749.6    87.9 1749.72    91.2 1750.13    98.2 1751.46   103.9 1752.26
     121 1753.64   126.5 1754.95   132.9 1757.18   137.1 1758.42   139.5 1758.92
#Mann= 3 ,-1,0
       0      .1       0    47.4    .045       0   59.79      .1       0
Bank Sta=47.4,59.79
XS Rating Curve= 0 ,0
Exp/Cntr(USF)=0,0
Exp/Cntr=0.3,0.1

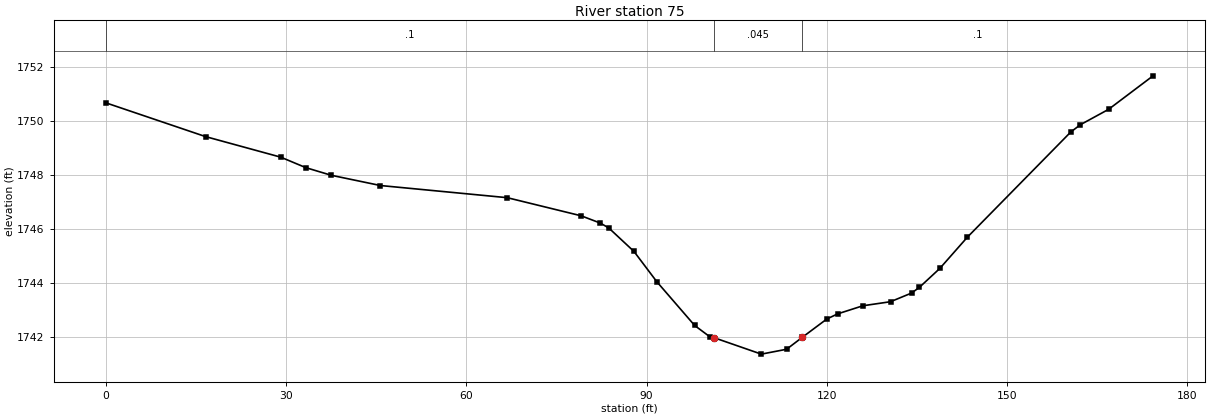
Type RM Length L Ch R = 1 ,75      ,,,
XS GIS Cut Line= 4
2235779.39744412737857.105737704 2235795.2812051737803.239070028
2235771.11026448737732.7980430672235733.81795609 737710.00829905
#Sta/Elev= 30
       0 1750.66    16.6 1749.41    29.1 1748.65    33.3 1748.26    37.5 1747.98
    45.7  1747.6    66.8 1747.15    79.1 1746.48    82.3 1746.21    83.7 1746.03
    87.9 1745.16    91.7 1744.04      98 1742.42   100.6 1741.99   101.2 1741.97
   109.1 1741.36   113.3 1741.54  115.911741.981     120 1742.66   121.8 1742.85
     126 1743.15   130.6  1743.3   134.1 1743.62   135.4 1743.83   138.8 1744.53
   143.4 1745.69   160.6 1749.58   162.2 1749.85   166.9 1750.42   174.3 1751.66
#Mann= 3 ,-1,0
       0      .1       0   101.2    .045       0  115.91      .1       0
Bank Sta=101.2,115.91
XS Rating Curve= 0 ,0
Exp/Cntr(USF)=0,0
Exp/Cntr=0.3,0.1
LCMann Table=0

Chan Stop Cuts=-1
Use User Specified Reach Order=0
Composite Channel Slope=5